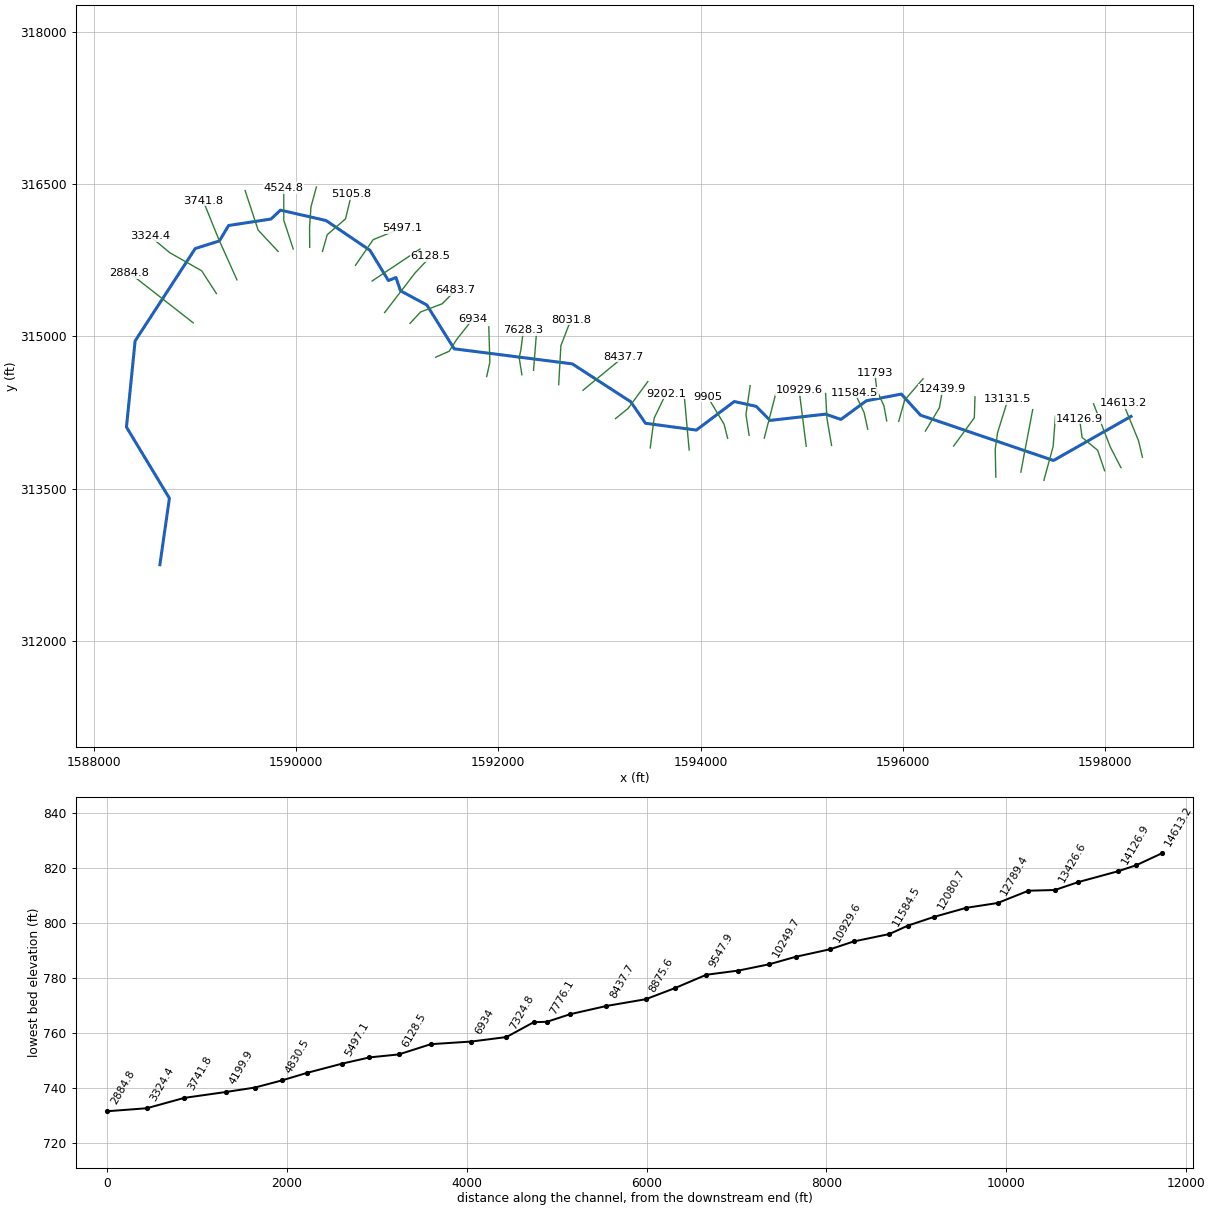
--- CMPMTKRN.prj (project) ---

Proj Title=CMPMTKRN
Current Plan=p01
Default Exp/Contr=0,0
English Units
Geom File=g01
Flow File=f01
Plan File=p01
BEGIN DESCRIPTION:
END DESCRIPTION:
DSS Export Rating Curves= 0
DSS Export Rating Curve Sorted= 0
DSS Export Volume Flow Curves= 0
DXF OffsetX= 0
DXF OffsetY= 0
DXF ScaleX= 0
DXF ScaleY= 0

--- CMPMTKRN.p01 (plan) ---

Plan Title=Floodplain
Program Version=4.00
Geom File=g01
Flow File=f01
K Sum by GR=0
Std Step Tol=0.01
Critical Tol=0.01
Num of Std Step Trials=20
Max Error Tol=0.3
Flow Tol Ratio=0.001
Split Flow NTrial=30
Split Flow Tol=0.02
Split Flow Ratio=0.02
Log Output Level=0
Friction Slope Method=1
Unsteady Friction Slope Method=2
Unsteady Bridges Friction Slope Method=1
Global Log Level=0
CheckData=False
Run HTab=0
Run UNet=0
Run PostProcess=0
UNET Theta=0
UNET Theta Warmup=0
UNET ZTol=0
UNET ZSATol=0
UNET MxIter=0
UNET MaxInSteps=0
UNET DtIC=0
UNET DtMin=0
UNET MaxCRTS=0
UNET WFStab=0
UNET SFStab=0
UNET WFX=0
UNET SFX=0
UNET DSS MLevel=0
UNET DZMax Abort=0
UNET Convert EG Bridges=0
UNET Use Existing IB Tables=0
UNET Froude Limit=0
UNET Froude Power=0
Write IC File=0
Echo Input=False
Echo Output=False
Write Detailed=0

--- CMPMTKRN.f01 (steady flow) ---

Flow Title=NFF Regression Equation
Program Version=4.10
Number of Profiles= 1
Profile Names=P100yr
River Rch & RM=CMPMTKRN,Main            ,14613.2
     858
River Rch & RM=CMPMTKRN,Main            ,14331.9
     907
River Rch & RM=CMPMTKRN,Main            ,12080.7
     956
River Rch & RM=CMPMTKRN,Main            ,11584.5
    1061
River Rch & RM=CMPMTKRN,Main            ,9905
    1073
River Rch & RM=CMPMTKRN,Main            ,5105.8
    1197
River Rch & RM=CMPMTKRN,Main            ,4830.5
    1539
River Rch & RM=CMPMTKRN,Main            ,579.6
    1662
Boundary for River Rch & Prof#=CMPMTKRN,Main            , 1
Up Type= 0
Dn Type= 3
Dn Slope=0.0001
DSS Import GetInterval= 0
DSS Import GetPeak= 0
DSS Import FillOption= 0

--- CMPMTKRN.g01 (geometry) ---

Geom Title=USGS 10m DEM
Program Version=4.10

River Reach=CMPMTKRN        ,Main
Reach XY= 30
     1598255.459      314212.817     1597489.124      313778.832
     1596174.864      314224.806     1595984.934      314432.445
     1595640.147      314366.931     1595387.711       314183.14
     1595234.239      314234.876     1594686.665      314173.321
     1594550.038      314311.612     1594333.024      314359.355
     1593958.458      314078.105     1593455.854      314144.945
     1593309.712      314356.698      1592731.37      314729.961
     1591563.927      314878.018     1591293.653      315309.389
     1591033.642      315448.974      1590988.33      315579.442
      1590913.33      315550.536     1590731.299      315847.671
     1590297.307      316140.804      1589846.49      316243.244
     1589753.434      316155.744     1589333.642      316091.856
     1589242.323      315940.119     1589003.781      315865.119
     1588409.352      314955.908     1588323.818      314107.132
      1588748.47      313407.115     1588654.118      312752.689

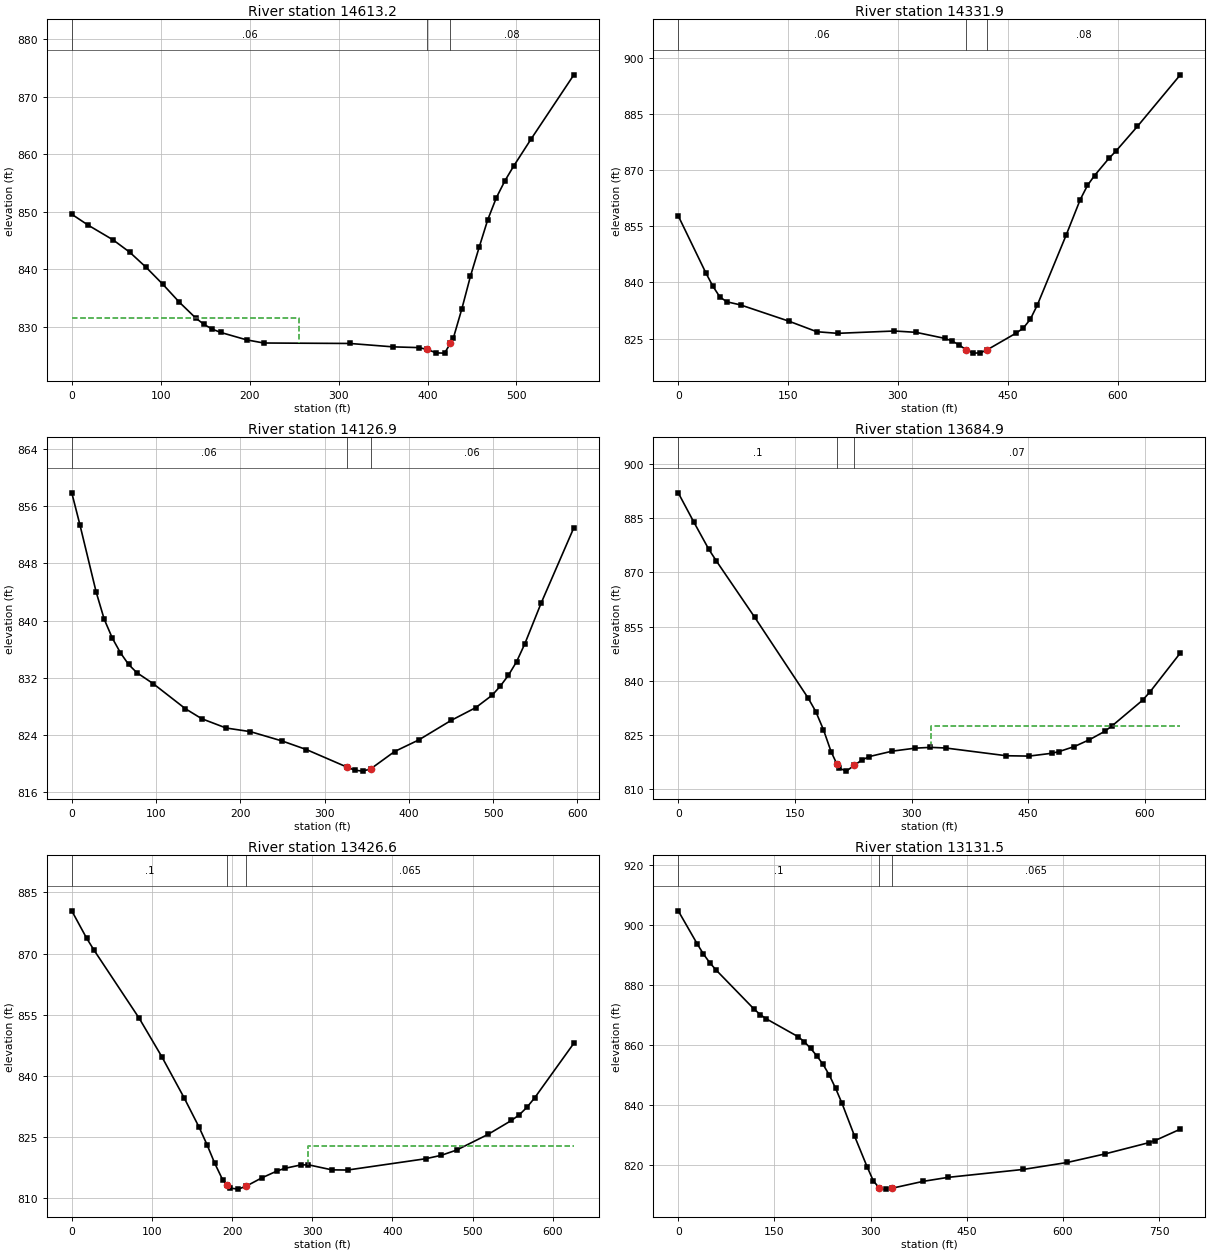
Type RM Length L Ch R = 1 ,14613.2 ,281.2,281.4,280.6
XS GIS Cut Line= 3
     1598368.853      313810.514     1598330.047       313973.38
     1598178.983      314340.612
#Sta/Elev= 30
       0  849.58    18.6  847.67    46.5  845.12    65.1  842.99    83.7  840.34
   102.3  837.42   120.9   834.3   139.5  831.52   148.8  830.42   158.1   829.6
   167.4  829.04   196.5  827.75   215.8   827.2   312.7  827.12   361.1  826.53
   390.2   826.4   399.9  826.08   409.6  825.48   419.2  825.44   425.8  827.18
   428.9  827.99   438.6  833.15   448.3  838.84     458  843.82   467.7  848.63
   477.4  852.47     487   855.4   496.7  857.92   516.1  862.58   564.5  873.82
#Mann= 3 , 0 , 0
       0     .06       0   399.9    .045       0   425.8     .08       0
#XS Ineff= 2 , 0
          255.06  831.47
Permanent Ineff=
       F       F
Bank Sta=399.9,425.8
XS Rating Curve= 0 ,0
Exp/Cntr=0.3,0.1

Type RM Length L Ch R = 1 ,14331.9 ,192.7,205,216.1
XS GIS Cut Line= 3
     1598156.179      313708.517     1598051.703      313910.034
      1597884.95      314337.264
#Sta/Elev= 30
       0  857.77    37.8  842.52    47.3     839    56.8  836.15    66.2  834.85
    85.1  834.01   151.3  829.66   189.2  826.86   217.5  826.43   295.3  827.05
   324.6   826.7   363.6   825.1   373.4  824.43   383.1   823.4   392.9  822.06
   402.6  821.15   412.4  821.21   422.2  822.07   461.2  826.47   470.9  827.77
   480.7  830.15   490.4     834   529.5  852.53     549  862.13   558.8  865.88
   568.5  868.53     588  873.08   597.8  875.07   627.1  881.65   685.6  895.39
#Mann= 3 , 0 , 0
       0     .06       0   392.9    .045       0   422.2     .08       0
Bank Sta=392.9,422.2
XS Rating Curve= 0 ,0
Exp/Cntr=0.3,0.1

Type RM Length L Ch R = 1 ,14126.9 ,467.6,442,414.9
XS GIS Cut Line= 4
     1597994.504      313678.136     1597926.302      313878.832
     1597772.269      314005.609     1597747.108      314188.118
#Sta/Elev= 30
       0  857.86     9.6  853.42    28.9     844    38.5  840.18    48.2  837.52
    57.8  835.48    67.4  833.86    77.1  832.72    96.4  831.19   134.9  827.66
   154.2  826.27   183.1  824.97     212  824.46     250  823.14   278.5  821.95
     326  819.53   335.5  819.08     345  818.94   354.5  819.24     383  821.68
   411.5  823.29   450.2  826.04   479.3  827.82   498.7  829.55   508.4  830.82
   518.1  832.35   527.8  834.25   537.5  836.74   556.9  842.44   595.7  852.98
#Mann= 3 , 0 , 0
       0     .06       0     326    .045       0   354.5     .06       0
Bank Sta=326,354.5
XS Rating Curve= 0 ,0
Exp/Cntr=0.3,0.1

Type RM Length L Ch R = 1 ,13684.9 ,256.4,258.3,260
XS GIS Cut Line= 3
     1597394.309      313583.776     1597485.486      313915.501
     1597508.393       314216.33
#Sta/Elev= 30
       0  892.05    19.7  884.09    39.3  876.42    49.2  873.13    98.3  857.61
   167.1  835.22   176.9  831.49   186.8  826.44   196.6  820.38   204.1  816.93
   206.4  815.87   216.2     815   226.1  816.56   235.9  818.04   245.7  819.03
   275.2  820.53   304.7  821.36   324.4  821.58     344   821.4   421.9  819.26
   451.1  819.16   480.3  819.94     490  820.43   509.5  821.81   528.9  823.71
   548.4     826   558.1  827.56   597.1  834.62   606.8  836.96   645.7  847.71
#Mann= 3 , 0 , 0
       0      .1       0   204.1    .045       0   226.1     .07       0
#XS Ineff= 2 , 0
                          324.72           827.5
Permanent Ineff=
       F       F
Bank Sta=204.1,226.1
XS Rating Curve= 0 ,0
Exp/Cntr=0.3,0.1

Type RM Length L Ch R = 1 ,13426.6 ,293.8,295.1,296
XS GIS Cut Line= 3
     1597166.596       313664.03     1597195.893       313820.28
     1597283.783      314279.264
#Sta/Elev= 30
       0  880.49    18.7  873.71      28  870.76    84.2  854.07   112.2   844.7
   140.3  834.51     159  827.27   168.7  823.05   178.4  818.45   188.2  814.43
     194   813.2   197.9  812.37   207.6  812.13   217.4  812.84   236.9  814.88
   256.3  816.61   266.1  817.25   285.5  818.06   295.3   818.1   324.5  816.86
     344  816.82   441.3  819.59   460.8  820.43   480.3  821.74   519.2  825.57
   548.4  828.99   558.2  830.38   567.9  832.25   577.6   834.6   626.3  847.96
#Mann= 3 , 0 , 0
       0      .1       0     194    .045       0   217.4    .065       0
#XS Ineff= 2 , 0
                          294.97           822.8
Permanent Ineff=
       F       F
Bank Sta=194,217.4
XS Rating Curve= 0 ,0
Exp/Cntr=0.3,0.1

Type RM Length L Ch R = 1 ,13131.5 ,353.2,342.1,331
XS GIS Cut Line= 4
       1596919.2      313615.202     1596913.243       313890.25
     1596936.561       314053.57     1597039.128      314380.918
#Sta/Elev= 30
       0  904.71    29.5  893.72    39.3   890.3    49.1  887.42      59  884.97
   117.9  872.01   127.7  870.12   137.6  868.65   186.7  862.75   196.5  861.06
   206.3  858.86   216.2  856.31     226  853.46   235.8  849.84   245.6  845.44
   255.5  840.45   275.1  829.52   294.5  819.37   304.2  814.67   313.9  812.14
   323.6  811.87   333.3  812.16   381.9  814.46   420.7  815.79   538.1  818.44
   606.7  820.76   665.5  823.61   734.1  827.37   743.9  828.09   783.1  831.88
#Mann= 3 , 0 , 0
       0      .1       0   313.9    .045       0   333.3    .065       0
Bank Sta=313.9,333.3
XS Rating Curve= 0 ,0
Exp/Cntr=0.3,0.1

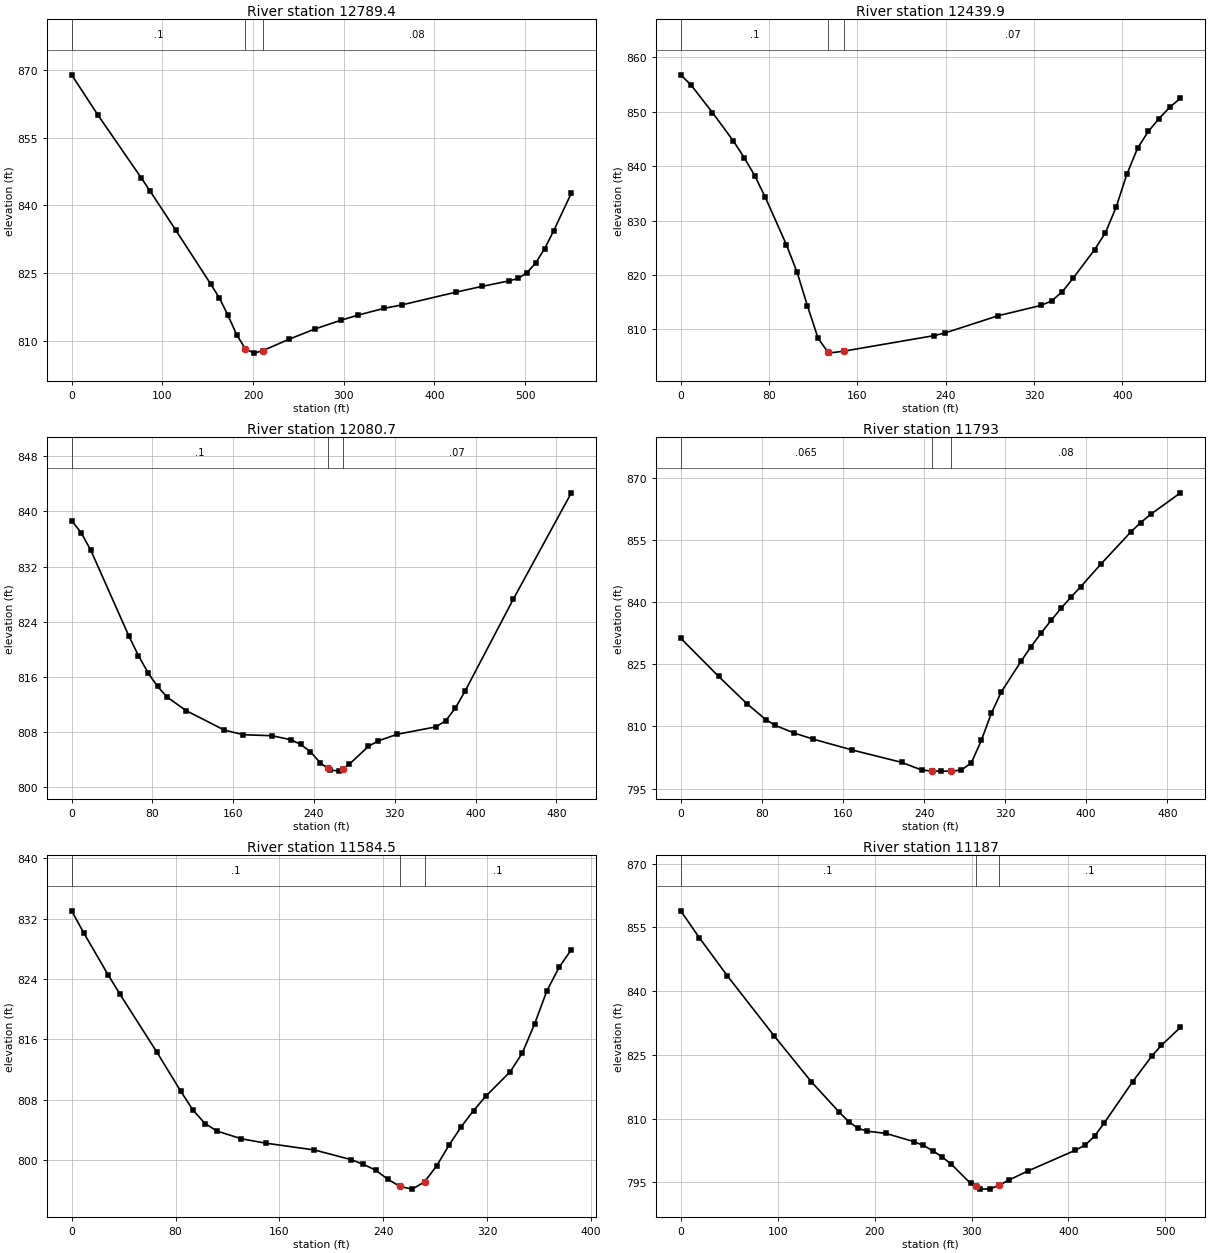
Type RM Length L Ch R = 1 ,12789.4 ,347.3,349.5,351.3
XS GIS Cut Line= 3
     1596502.533      313921.191     1596706.526      314198.969
     1596713.037      314405.132
#Sta/Elev= 27
       0  868.85    28.7  860.05    76.6  846.14    86.2  843.26   114.9  834.52
   153.2  822.69   162.7  819.63   172.3  815.76   181.9  811.46   191.5  808.35
     201   807.4   210.6  807.93   239.3  810.44     268  812.72   296.8  814.66
   315.9   815.8   344.6   817.3   364.3  818.06   423.2  820.84   452.7  822.15
   482.2  823.35     492  823.89   501.8  825.11   511.6  827.32   521.4  830.47
   531.3  834.36   550.9  842.74
#Mann= 3 , 0 , 0
       0      .1       0   191.5    .045       0   210.6     .08       0
Bank Sta=191.5,210.6
XS Rating Curve= 0 ,0
Exp/Cntr=0.3,0.1

Type RM Length L Ch R = 1 ,12439.9 ,361.7,359.2,354.4
XS GIS Cut Line= 3
     1596222.719      314068.682      1596361.39      314297.996
     1596392.851       314479.95
#Sta/Elev= 30
       0  856.75     9.6  854.82    28.7  849.83    47.8  844.58    57.4  841.57
      67  838.25    76.6  834.27    95.7  825.56   105.3  820.56   114.8  814.32
   124.4  808.37   133.2  805.88     134  805.65   148.2  806.03   229.7  808.87
   239.3  809.35   287.4  812.51   326.3  814.41     336  815.24   345.7  816.94
   355.4  819.41   374.9  824.66   384.6  827.73   394.3  832.41     404  838.45
   413.8  843.29   423.5  846.35   433.2  848.72   442.9  850.78   452.6  852.46
#Mann= 3 , 0 , 0
       0      .1       0   133.2    .045       0   148.2     .07       0
Bank Sta=133.2,148.2
XS Rating Curve= 0 ,0
Exp/Cntr=0.3,0.1

Type RM Length L Ch R = 1 ,12080.7 ,261.9,287.7,313.7
XS GIS Cut Line= 3
        1595959.      314163.899     1596018.028      314373.101
     1596199.452       314583.17
#Sta/Elev= 30
       0  838.65     9.4  836.91    18.9  834.38    56.7  821.92    66.2  819.07
    75.6  816.61    85.1  814.61    94.5  813.08   113.4  811.11   151.2  808.29
   170.1  807.62   198.5  807.47   217.4  806.88   226.9  806.21   236.5  805.15
   246.1  803.56   253.6  802.73   255.6  802.51   265.2  802.34   268.6  802.69
   274.8  803.32   293.9  805.93   303.5  806.72   322.6  807.69   360.9  808.76
   370.5  809.66   380.1  811.51   389.6  813.93   437.5   827.3   494.9  842.69
#Mann= 3 , 0 , 0
       0      .1       0   253.6    .045       0   268.6     .07       0
Bank Sta=253.6,268.6
XS Rating Curve= 0 ,0
Exp/Cntr=0.3,0.1

Type RM Length L Ch R = 1 ,11793   ,207.9,208.5,208.6
XS GIS Cut Line= 4
     1595840.077      314169.108     1595813.167      314315.809
     1595743.723      314467.719     1595722.021      314643.066
#Sta/Elev= 30
       0  831.32    37.3  822.11    65.2  815.52    83.9  811.65    93.2  810.26
   111.9   808.4   130.5  806.94   168.8  804.33   217.9  801.32   237.6  799.47
   247.4  799.21   257.2   799.2     267   799.2   276.9  799.46   286.7  801.22
   296.5  806.61   306.4  813.18   316.2  818.34   335.8  825.79   345.6  829.31
   355.4  832.54   365.3  835.63   375.1  838.54   384.9  841.24   394.7   843.8
   414.3   849.2   443.8  856.96   453.6  859.25   463.4  861.23   492.9  866.46
#Mann= 3 , 0 , 0
       0    .065       0   247.4    .045       0     267     .08       0
Bank Sta=247.4,267
XS Rating Curve= 0 ,0
Exp/Cntr=0.3,0.1

Type RM Length L Ch R = 1 ,11584.5 ,406.4,397.5,387.7
XS GIS Cut Line= 3
     1595652.857      314086.535     1595616.686      314250.645
     1595523.814        314446.4
#Sta/Elev= 30
       0  833.05     9.3  830.12      28  824.58    37.3  821.95    65.4  814.35
      84   809.1    93.4   806.6   102.7  804.81     112  803.81   130.7  802.79
   149.4  802.21   186.9  801.31   215.2  800.02   224.6   799.4     234  798.63
   243.4  797.42   252.8  796.46   262.2  796.11   271.7  797.08   281.1  799.23
   290.5  801.94   299.9  804.39   309.4  806.54   318.8  808.44   337.6  811.69
     347   814.2   356.5  818.08   365.9  822.45   375.3  825.56   384.7   827.9
#Mann= 3 , 0 , 0
       0      .1       0   252.8    .045       0   271.7      .1       0
Bank Sta=252.8,271.7
XS Rating Curve= 0 ,0
Exp/Cntr=0.3,0.1

Type RM Length L Ch R = 1 ,11187   ,255.5,257.4,259
XS GIS Cut Line= 3
     1595294.916      313927.242     1595249.493      314192.851
     1595235.888      314438.527
#Sta/Elev= 30
       0  858.89    19.2  852.56    48.1  843.59    96.2  829.52   134.7  818.69
   163.6   811.5   173.2  809.32   182.8  807.73   192.5  807.04   211.7  806.52
   240.6  804.58   250.2   803.7   259.8  802.49   269.5  801.01   279.3  799.24
     299  794.75   304.1  794.05   308.8  793.41   318.7  793.45   328.5  794.31
   338.4  795.53     358  797.66   407.2  802.57   417.1  803.75   426.9  805.87
   436.8  808.96   466.3  818.72     486  824.72   495.8  827.22   515.5  831.49
#Mann= 3 , 0 , 0
       0      .1       0   304.1    .045       0   328.5      .1       0
Bank Sta=304.1,328.5
XS Rating Curve= 0 ,0
Exp/Cntr=0.3,0.1

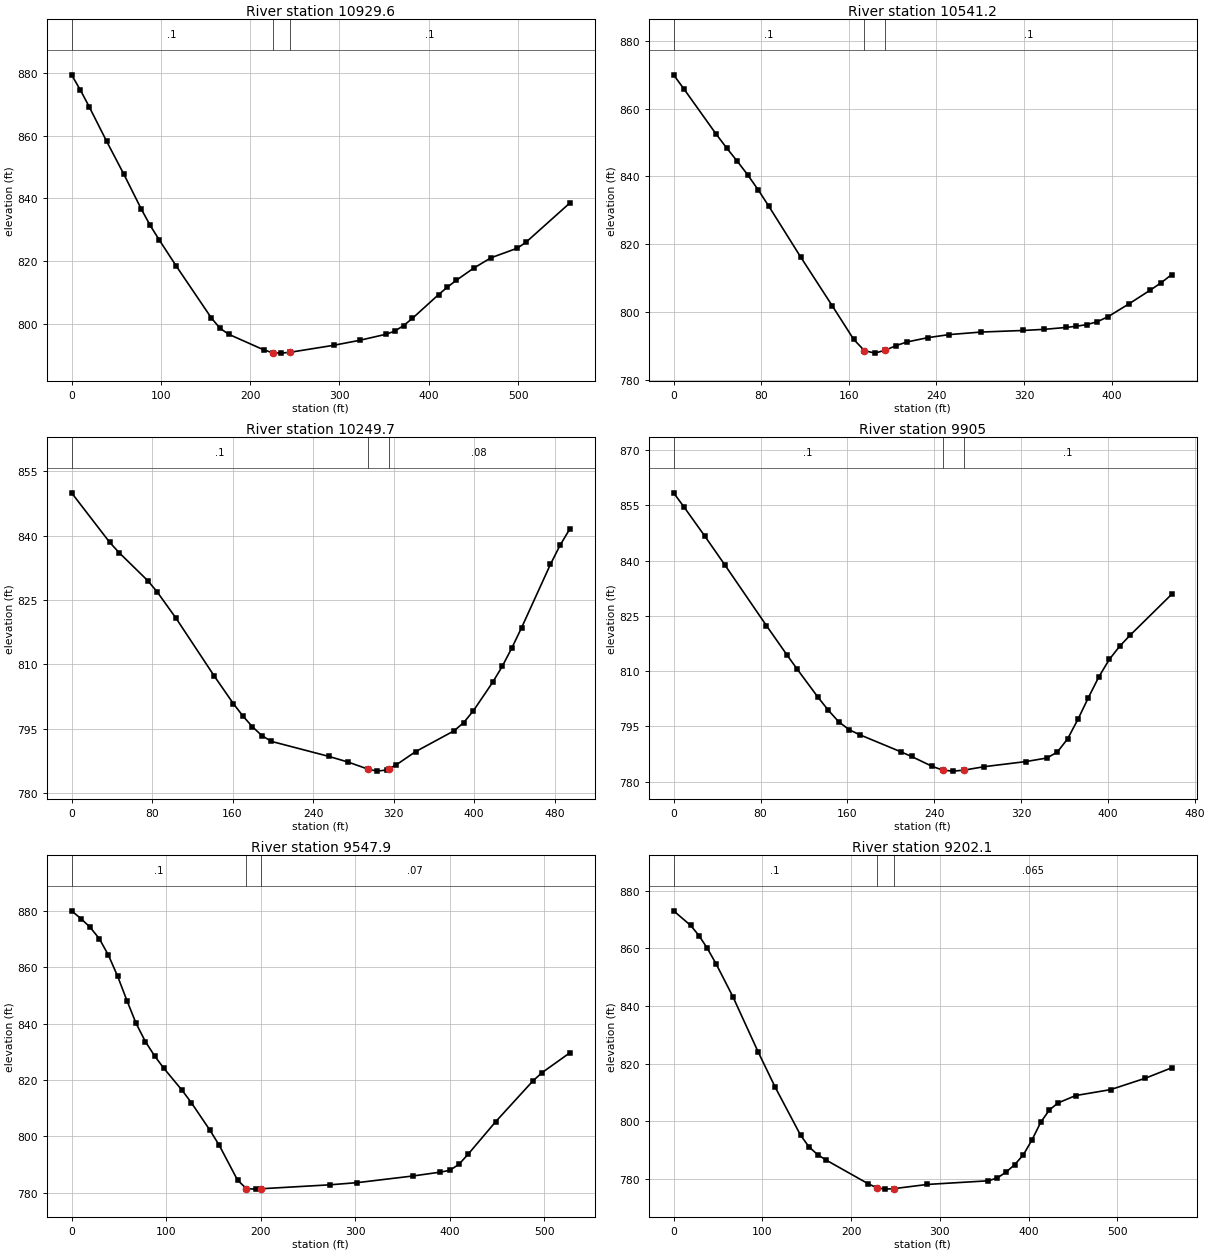
Type RM Length L Ch R = 1 ,10929.6 ,397,388.5,378.6
XS GIS Cut Line= 2
       1595044.5      313918.222       1594974.4      314471.655
#Sta/Elev= 30
       0  879.42     9.8   874.6    19.6  869.31    39.2  858.25    58.7  847.62
    78.3  836.46    88.1  831.35    97.9  826.86   117.4  818.33   156.6  801.82
   166.4  798.49   176.2   796.6   215.3  791.65   225.1  790.74   234.9  790.61
   244.7  790.88   293.6  793.11     323  794.72   352.3  796.64   362.1  797.66
   371.9   799.4   381.7  801.69     411  809.28   420.8  811.64   430.6  813.79
   450.2   817.7   469.8  821.04   499.1  824.09   508.9  825.98   557.8  838.45
#Mann= 3 , 0 , 0
       0      .1       0   225.1    .045       0   244.7      .1       0
Bank Sta=225.1,244.7
XS Rating Curve= 0 ,0
Exp/Cntr=0.3,0.1

Type RM Length L Ch R = 1 ,10541.2 ,288.1,291.4,293.9
XS GIS Cut Line= 2
     1594629.552      313998.857     1594744.135      314438.961
#Sta/Elev= 30
       0     870     9.7  865.71    38.7  852.56    48.4  848.42    58.1   844.5
    67.7  840.46    77.4  835.96    87.1  831.13   116.1  816.17   145.1  801.69
   164.5  791.86   174.2  788.57   183.8  787.82   193.5  788.71   203.2  790.04
   212.9   791.1   232.2  792.39   251.6  793.29   280.6  794.04   319.3  794.51
   338.7  794.85     358  795.39   367.7  795.76   377.4  796.24     387   797.1
   396.7  798.57   416.1  802.42   435.4  806.45   445.1  808.57   454.8     811
#Mann= 3 , 0 , 0
       0      .1       0   174.2    .045       0   193.5      .1       0
Bank Sta=174.2,193.5
XS Rating Curve= 0 ,0
Exp/Cntr=0.3,0.1

Type RM Length L Ch R = 1 ,10249.7 ,328.6,344.8,359.2
XS GIS Cut Line= 3
     1594479.812      314026.201     1594448.562       314231.93
     1594490.229      314515.784
#Sta/Elev= 30
       0  849.98    37.8  838.47    47.3  836.03    75.7  829.52    85.1  826.89
     104   820.7   141.9  807.26   160.8  800.86   170.2     798   179.7  795.48
   189.2   793.4   198.6  792.06   255.9  788.55     275  787.23   294.2  785.63
   303.7  785.13   313.3   785.4     315  785.62   322.8  786.61     342  789.68
   380.2  794.53   389.8  796.45   399.4  799.21   418.5  805.82     428  809.52
   437.6  813.84   447.2  818.52   475.9  833.29   485.4  837.71     495  841.48
#Mann= 3 , 0 , 0
       0      .1       0   294.2    .045       0     315     .08       0
Bank Sta=294.2,315
XS Rating Curve= 0 ,0
Exp/Cntr=0.3,0.1

Type RM Length L Ch R = 1 ,9905    ,367.3,357.1,347.5
XS GIS Cut Line= 3
     1594267.572      313997.555     1594232.416      314135.576
     1594069.656      314406.409
#Sta/Elev= 30
       0  858.41     9.5   854.6    28.5  846.75    47.5  838.69    85.5  822.32
   104.4  814.36   113.9  810.46   132.9  802.89   142.4  799.36     152  796.22
   161.6  794.07   171.2  792.72   209.4  788.04     219   786.8   238.2  784.09
   247.8  783.09   257.3  782.82   266.9  783.07     286  784.03   324.4  785.42
   343.5  786.38   353.1  787.97   362.6  791.56   372.2  796.91   381.8   802.8
   391.4  808.42     401  813.14   410.5  816.72   420.1  819.71   458.4  830.84
#Mann= 3 , 0 , 0
       0      .1       0   247.8    .045       0   266.9      .1       0
Bank Sta=247.8,266.9
XS Rating Curve= 0 ,0
Exp/Cntr=0.3,0.1

Type RM Length L Ch R = 1 ,9547.9  ,350.7,345.8,340.6
XS GIS Cut Line= 2
     1593887.126      313881.529     1593839.362      314406.425
#Sta/Elev= 30
       0  880.12     9.8  877.38    19.5  874.34    29.3  870.25      39  864.38
    48.8  856.85    58.6  848.25    68.3  840.14    78.1  833.71    87.8  828.64
    97.6  824.24   117.1  816.34   126.9  811.93   146.4  802.24   156.2  796.92
   175.7  784.49   185.1  781.46   195.2   781.3   200.1  781.42   273.3  782.83
   302.6  783.61   361.1  785.96   390.4  787.34   400.2  787.97   409.9  790.08
   419.7   793.7     449   805.3     488  819.63   497.8  822.63   527.1  829.64
#Mann= 3 , 0 , 0
       0      .1       0   185.1    .045       0   200.1     .07       0
Bank Sta=185.1,200.1
XS Rating Curve= 0 ,0
Exp/Cntr=0.3,0.1

Type RM Length L Ch R = 1 ,9202.1  ,337.5,326.4,314.3
XS GIS Cut Line= 3
     1593501.947      313902.503      1593541.01      314195.471
     1593656.875       314434.32
#Sta/Elev= 30
       0  872.96    19.1  867.93    28.6  864.38    38.1   859.9    47.7  854.68
    66.7  843.25    95.3  824.01   114.4  811.84     143  795.19   152.6  791.09
   162.1  788.48   171.6  786.59   219.3  778.32   228.8  776.97   238.4  776.48
   247.9  776.64     286  778.11   354.6  779.37   364.4  780.34   374.2  782.29
     384  784.89   393.9  788.34   403.7  793.55   413.6  799.68   423.4  803.97
   433.2  806.38   452.9  808.92   492.2  810.97   531.5  814.94     561  818.53
#Mann= 3 , 0 , 0
       0      .1       0   228.8    .045       0   247.9    .065       0
Bank Sta=228.8,247.9
XS Rating Curve= 0 ,0
Exp/Cntr=0.3,0.1

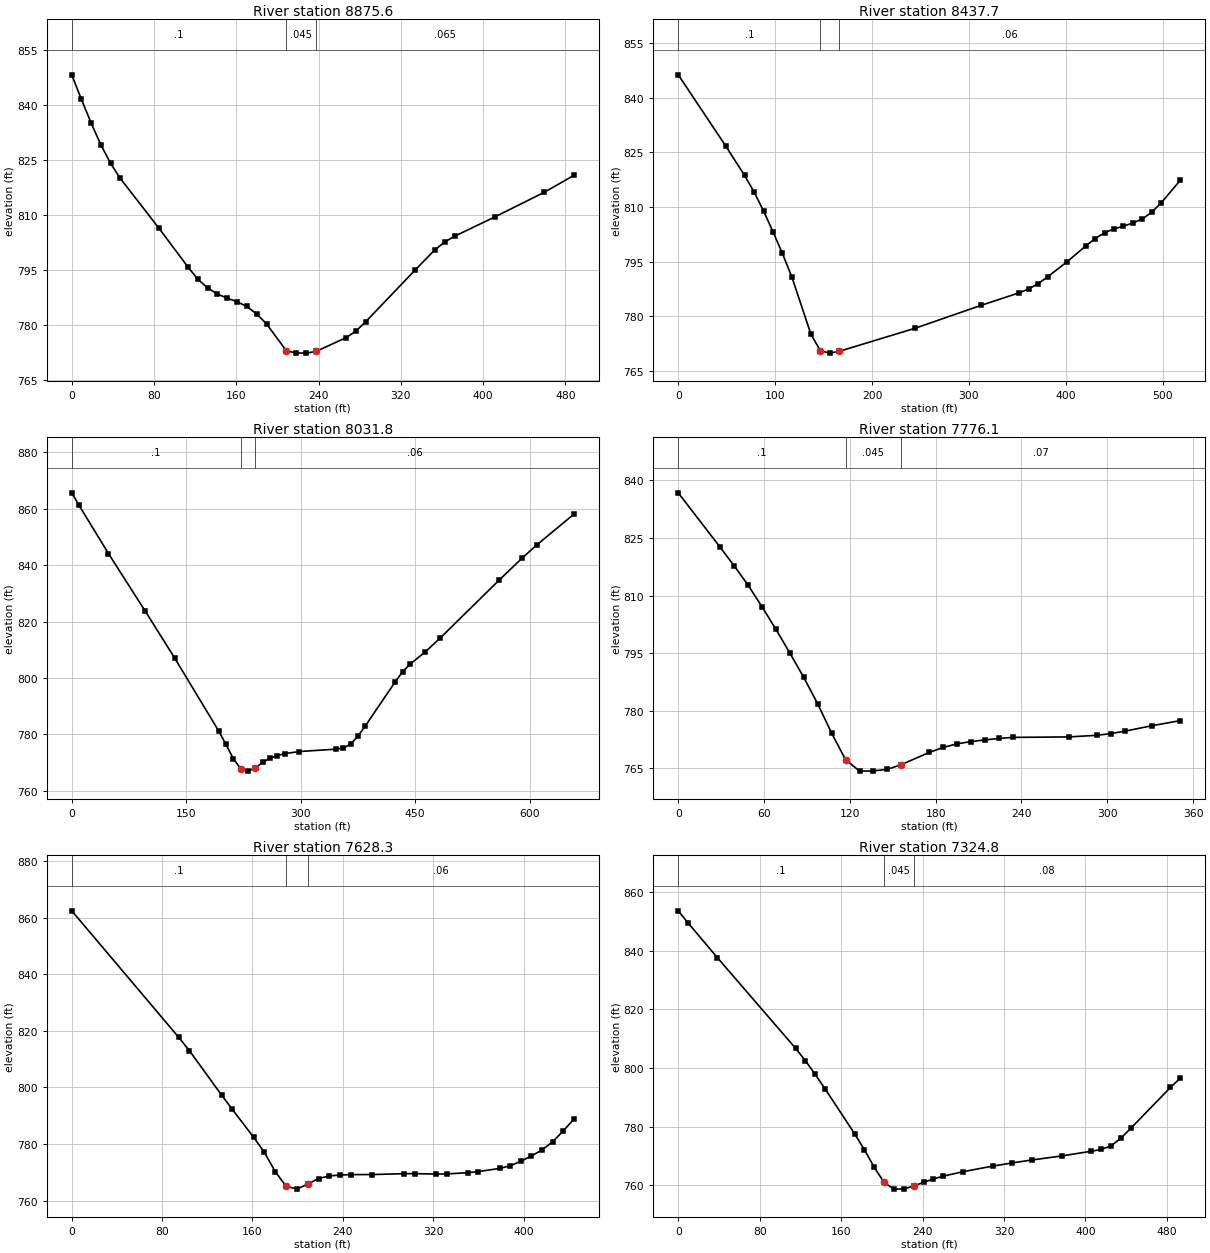
Type RM Length L Ch R = 1 ,8875.6  ,443.5,438,432.2
XS GIS Cut Line= 3
     1593158.813      314190.951     1593283.813      314291.646
     1593478.258      314555.535
#Sta/Elev= 30
       0  848.26     9.4  841.54    18.9  835.08    28.3  829.18    37.8   824.1
    47.2  820.02      85  806.38   113.3  795.77   122.8  792.49   132.2  790.16
   141.6  788.52   151.1   787.4   160.5  786.46   170.2  785.12   179.8   783.1
   189.4  780.39   208.7  773.04   218.4  772.45     228  772.41   237.6  772.88
   266.6   776.6   276.2  778.38   285.8  780.94     334  795.08   353.3  800.61
     363  802.75   372.6   804.3   411.2   809.5   459.4  816.22   488.3  820.85
#Mann= 3 , 0 , 0
       0      .1       0   208.7    .045       0   237.6    .065       0
Bank Sta=208.7,237.6
XS Rating Curve= 0 ,0
Exp/Cntr=0.3,0.1

Type RM Length L Ch R = 1 ,8437.7  ,387,405.8,424.4
XS GIS Cut Line= 2
     1592837.259      314469.746      1593237.57      314798.662
#Sta/Elev= 29
       0  846.25    48.9  826.77    68.4   818.7    78.2  814.17      88  808.96
    97.8  803.22   107.5  797.28   117.3  790.78   136.9  775.14   146.6  770.64
   156.4  769.95   166.2  770.45   244.4  776.77   312.8  783.07   351.9  786.49
   361.7  787.56   371.5  789.03   381.2  790.86   400.8  794.91   420.4   799.3
   430.1  801.34   439.9  802.95   449.7  804.01   459.4  804.77   469.2  805.64
     479  806.75   488.8  808.62   498.6  811.23   518.1  817.34
#Mann= 3 , 0 , 0
       0      .1       0   146.6    .045       0   166.2     .06       0
Bank Sta=146.6,166.2
XS Rating Curve= 0 ,0
Exp/Cntr=0.3,0.1

Type RM Length L Ch R = 1 ,8031.8  ,256.1,255.7,255
XS GIS Cut Line= 3
      1592597.25      314525.405     1592618.948      314909.537
     1592717.913      315164.114
#Sta/Elev= 30
       0  865.68     9.6   861.2    48.1  844.13    96.2  823.73   134.7  807.13
   192.4  781.24     202  776.46   211.6  771.41   221.2  767.83   230.8  766.94
   240.5   768.1   250.1  770.04   259.7  771.52   269.3  772.46   278.9  773.14
   298.2  773.89   346.3  774.74   355.9  775.14   365.5  776.52   375.1  779.39
   384.7     783   423.8  798.61   433.5   802.2   443.3   804.9   462.8  809.15
   482.3  814.03   560.3  834.79   589.6  842.38   609.1  847.14   657.9  858.09
#Mann= 3 , 0 , 0
       0      .1       0   221.2    .045       0   240.5     .06       0
Bank Sta=221.2,240.5
XS Rating Curve= 0 ,0
Exp/Cntr=0.3,0.1

Type RM Length L Ch R = 1 ,7776.1  ,151,147.8,144.7
XS GIS Cut Line= 2
     1592348.118      314665.952     1592376.284      315015.893
#Sta/Elev= 28
       0  836.78    29.3  822.59      39   817.8    48.8  812.72    58.5  807.12
    68.3  801.19      78  795.03    87.8  788.63    97.5  781.77   107.3  774.08
     117   767.2   126.8   764.2   136.5  764.25   146.3  764.68     156   765.9
   175.5  769.07   185.3  770.38   195.1771.3359   204.8   771.9   214.5  772.35
   224.3  772.73     234     773   273.1  773.12   292.6  773.54   302.3  773.98
   312.1   774.6   331.6  776.07   351.1  777.37
#Mann= 3 , 0 , 0
       0      .1       0     117    .045       0     156     .07       0
Bank Sta=117,156
XS Rating Curve= 0 ,0
Exp/Cntr=0.3,0.1

Type RM Length L Ch R = 1 ,7628.3  ,297.3,303.5,308.7
XS GIS Cut Line= 4
     1592233.225      314623.082     1592206.434      314791.418
     1592223.196      314866.455     1592248.257      315061.983
#Sta/Elev= 30
       0  862.44    94.7  817.71   104.2  812.96   132.6  797.31     142  792.31
     161  782.38   170.5  777.07   180.1  770.23   189.7   765.1   199.3  764.04
   208.9  765.85   218.5  767.78   228.1  768.71   237.7  769.02   247.3  769.17
   266.1   769.2   294.3   769.5   303.7  769.51   322.4  769.37   331.8  769.41
   350.6  769.85     360  770.25   378.8  771.35   388.2   772.3   397.5  773.88
   406.9  775.77   416.3  777.88   425.7  780.77   435.1  784.61   444.5  788.77
#Mann= 3 , 0 , 0
       0      .1       0   189.7    .045       0   208.9     .06       0
Bank Sta=189.7,208.9
XS Rating Curve= 0 ,0
Exp/Cntr=0.3,0.1

Type RM Length L Ch R = 1 ,7324.8  ,404.2,390.8,377.1
XS GIS Cut Line= 3
     1591885.369      314605.233     1591916.619      314745.858
     1591906.202      315094.816
#Sta/Elev= 29
       0  853.63     9.6  849.53    38.4  837.66   115.2  806.74   124.8  802.53
   134.4  797.87   144.1  792.94   173.2  777.58   182.8  772.13   192.5  766.11
   202.2  760.94   211.9  758.64   221.6  758.69   231.3   759.7     241  760.96
   250.7  762.11   260.4  763.07   279.8  764.59   308.9   766.5   328.3   767.6
   347.7   768.6   376.8  769.97   405.9  771.58   415.6  772.18   425.3  773.46
     435  776.07   444.7  779.46   483.5  793.34   493.2  796.54
#Mann= 3 , 0 , 0
       0      .1       0   202.2    .045       0   231.3     .08       0
Bank Sta=202.2,231.3
XS Rating Curve= 0 ,0
Exp/Cntr=0.3,0.1

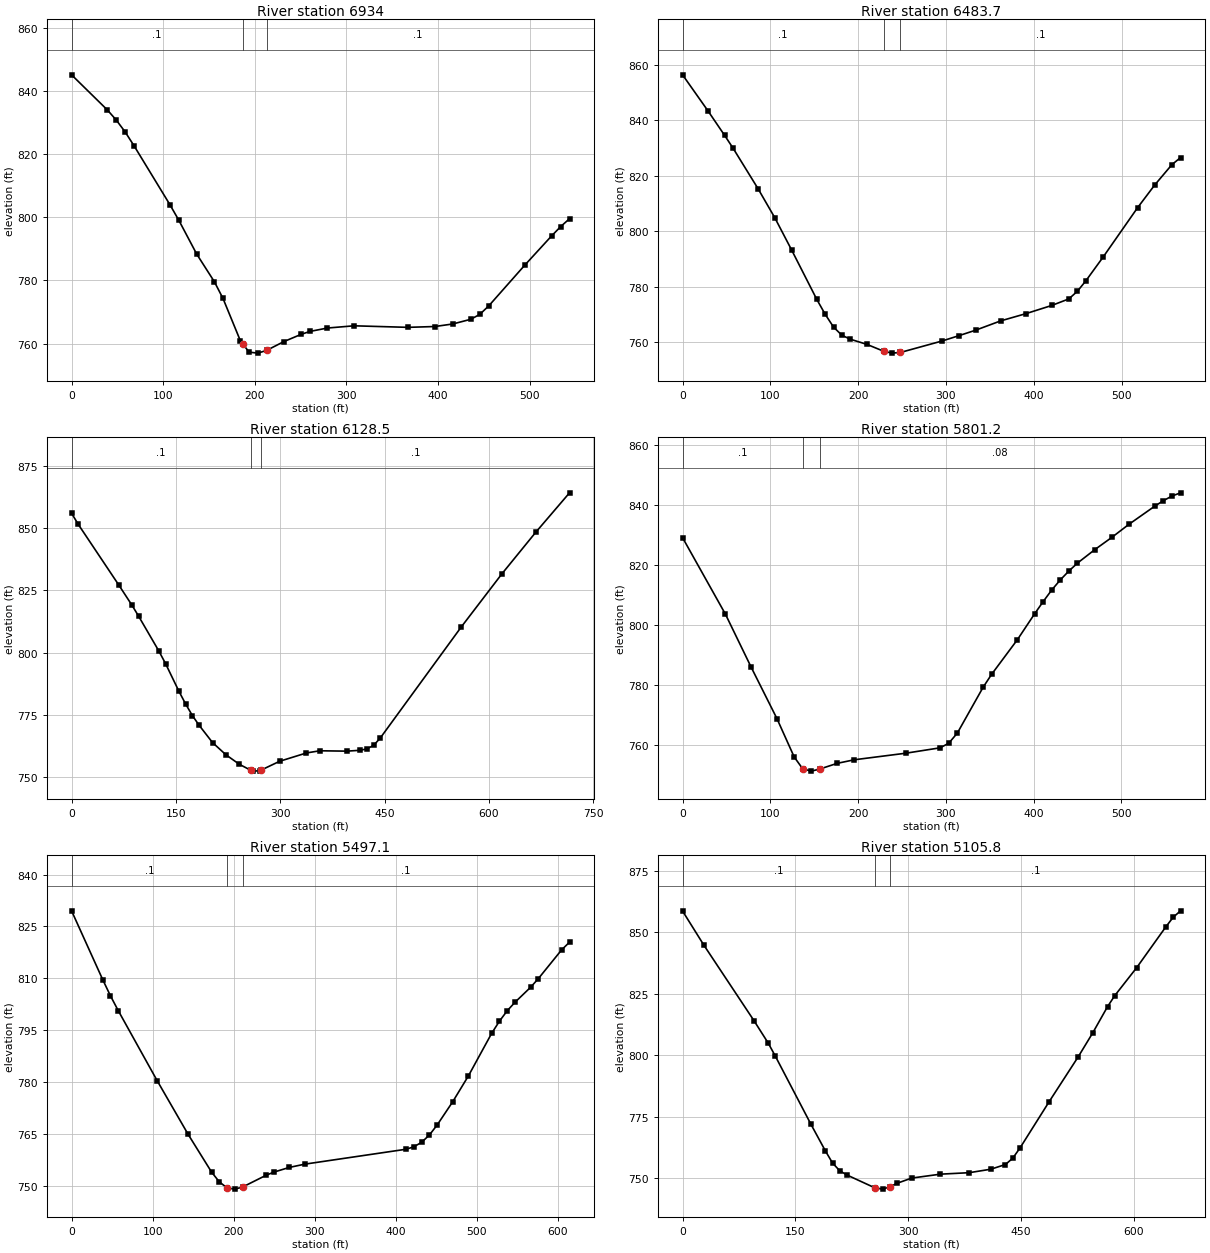
Type RM Length L Ch R = 1 ,6934    ,464.6,450.4,435.8
XS GIS Cut Line= 4
     1591380.161      314795.337     1591514.275      314853.931
     1591591.098      314973.723     1591749.952      315172.941
#Sta/Elev= 30
       0   845.1      39     834    48.8  830.78    58.5  827.02    68.3  822.59
   107.3  804.02   117.1  799.05   136.6  788.35   155.8  779.64   165.3  774.31
   184.3  760.88     187  759.87   193.8  757.32   203.3  757.01   212.8  757.86
   231.7  760.66   250.7  762.97   260.2  763.88   279.2  764.95   308.3  765.66
   367.1  765.17   396.5  765.43   416.1  766.24   435.7  767.72   445.5  769.26
   455.3  771.95   494.5   784.8   523.9   794.1   533.7  797.02   543.5  799.56
#Mann= 3 , 0 , 0
       0      .1       0     187    .045       0   212.8      .1       0
Bank Sta=187,212.8
XS Rating Curve= 0 ,0
Exp/Cntr=0.3,0.1

Type RM Length L Ch R = 1 ,6483.7  ,342.2,355.2,368
XS GIS Cut Line= 4
     1591127.556       315128.67     1591231.723       315240.65
     1591445.265      315321.379     1591576.775      315452.889
#Sta/Elev= 30
       0   856.3    28.7  843.43    47.8  834.54    57.4  829.94      86  815.27
   105.1   804.8   124.3  793.16   152.9   775.4   162.4  770.07     172  765.42
   181.5  762.49     191  761.07     210   759.2     229  756.74   238.6  756.05
   248.1  756.29   295.6  760.42   314.6  762.32   333.7   764.3   362.2  767.65
     391  770.26   420.4  773.21     440  775.58   449.8  778.36   459.5  782.15
   479.1  790.68   518.3  808.44   537.8  816.61   557.4  823.95   567.2  826.48
#Mann= 3 , 0 , 0
       0      .1       0     229    .045       0   248.1      .1       0
Bank Sta=229,248.1
XS Rating Curve= 0 ,0
Exp/Cntr=0.3,0.1

Type RM Length L Ch R = 1 ,6128.5  ,334.3,327.3,318.3
XS GIS Cut Line= 3
     1590876.357      315234.877     1591176.928       315624.74
     1591330.772      315787.102
#Sta/Elev= 30
       0  855.99     9.6  851.52    67.6  827.26    86.9     819    96.5  814.56
   125.5  800.61   135.1  795.57   154.4  784.41   164.1  779.27   173.7  774.67
   183.4  770.76   202.7  763.81     222  758.89   241.3  755.07   257.8  752.66
   260.6  752.33   270.3  752.47   272.8  752.78   299.2  756.29   337.8  759.64
   357.1  760.51   395.8  760.36   415.1  760.71   424.7  761.28   434.4   762.7
     444  765.68   560.4   810.3   618.7   831.6   667.3  848.29     716  864.19
#Mann= 3 , 0 , 0
       0      .1       0   257.8    .045       0   272.8      .1       0
Bank Sta=257.8,272.8
XS Rating Curve= 0 ,0
Exp/Cntr=0.3,0.1

Type RM Length L Ch R = 1 ,5801.2  ,295.1,304.1,312.6
XS GIS Cut Line= 3
      1590752.43      315545.538     1591224.963      315859.703
     1591224.963      315859.703
#Sta/Elev= 30
       0  829.14    48.9  803.58    78.3  785.84   107.6  768.73   127.2  755.96
     137  751.97   146.8  751.24   156.5  751.95   176.1  753.83   195.7  755.03
   254.4  757.22   293.5  759.02   303.3  760.55   313.1  763.94   342.4  779.19
   352.2  783.56   381.6  795.13   401.1  803.71   410.9  807.81   420.7  811.69
   430.5  815.07   440.2  818.01     450  820.66   469.6  825.12   489.2  829.25
   508.7  833.61   538.1  839.66   547.9  841.49   557.7  843.03   567.4   844.1
#Mann= 3 , 0 , 0
       0      .1       0     137    .045       0   156.5     .08       0
Bank Sta=137,156.5
XS Rating Curve= 0 ,0
Exp/Cntr=0.3,0.1

Type RM Length L Ch R = 1 ,5497.1  ,396.6,391.3,385.2
XS GIS Cut Line= 3
     1590588.494      315700.285     1590762.973      315952.889
     1591048.129      316067.473
#Sta/Elev= 30
       0   829.5    38.4  809.61      48  804.89    57.6  800.61   105.5  780.39
   143.9  764.78   172.7  753.91   182.3  751.06   191.9  749.32   201.5  748.97
   211.1  749.59   239.8  752.96   249.4  753.88   268.6  755.25   287.8   756.2
   412.6  760.51   422.2  761.21   431.8  762.51   441.5  764.65   451.1  767.56
   470.3  774.29   489.5  781.71   518.3  794.07   527.9  797.59   537.5   800.6
   547.1  803.06   566.3  807.38   575.9   809.9   604.7  818.24   614.3  820.43
#Mann= 3 , 0 , 0
       0      .1       0   191.9    .045       0   211.1      .1       0
Bank Sta=191.9,211.1
XS Rating Curve= 0 ,0
Exp/Cntr=0.3,0.1

Type RM Length L Ch R = 1 ,5105.8  ,257.2,275.2,292.7
XS GIS Cut Line= 4
     1590261.671      315837.004     1590308.546      316001.066
     1590489.536      316157.316     1590549.431      316402.108
#Sta/Elev= 30
       0  858.58    28.4  844.68    94.8   814.1   113.8  804.95   123.2  799.69
   170.6  771.96   189.8  761.15   199.3  756.22   208.9  753.07   218.4  751.36
   255.8   746.1   266.3  745.61   275.8  746.59   285.4  748.02   304.5   750.1
   342.8  751.69     381  752.29   409.7   753.7   429.1  755.61   438.8  758.16
   448.5  762.34   487.3  781.18     526  799.44   545.4  809.22   564.8  819.73
   574.5  824.25   603.6   835.6   642.4   852.2     652  856.02   661.8  858.66
#Mann= 3 , 0 , 0
       0      .1       0   255.8    .045       0   275.8      .1       0
Bank Sta=255.8,275.8
XS Rating Curve= 0 ,0
Exp/Cntr=0.3,0.1

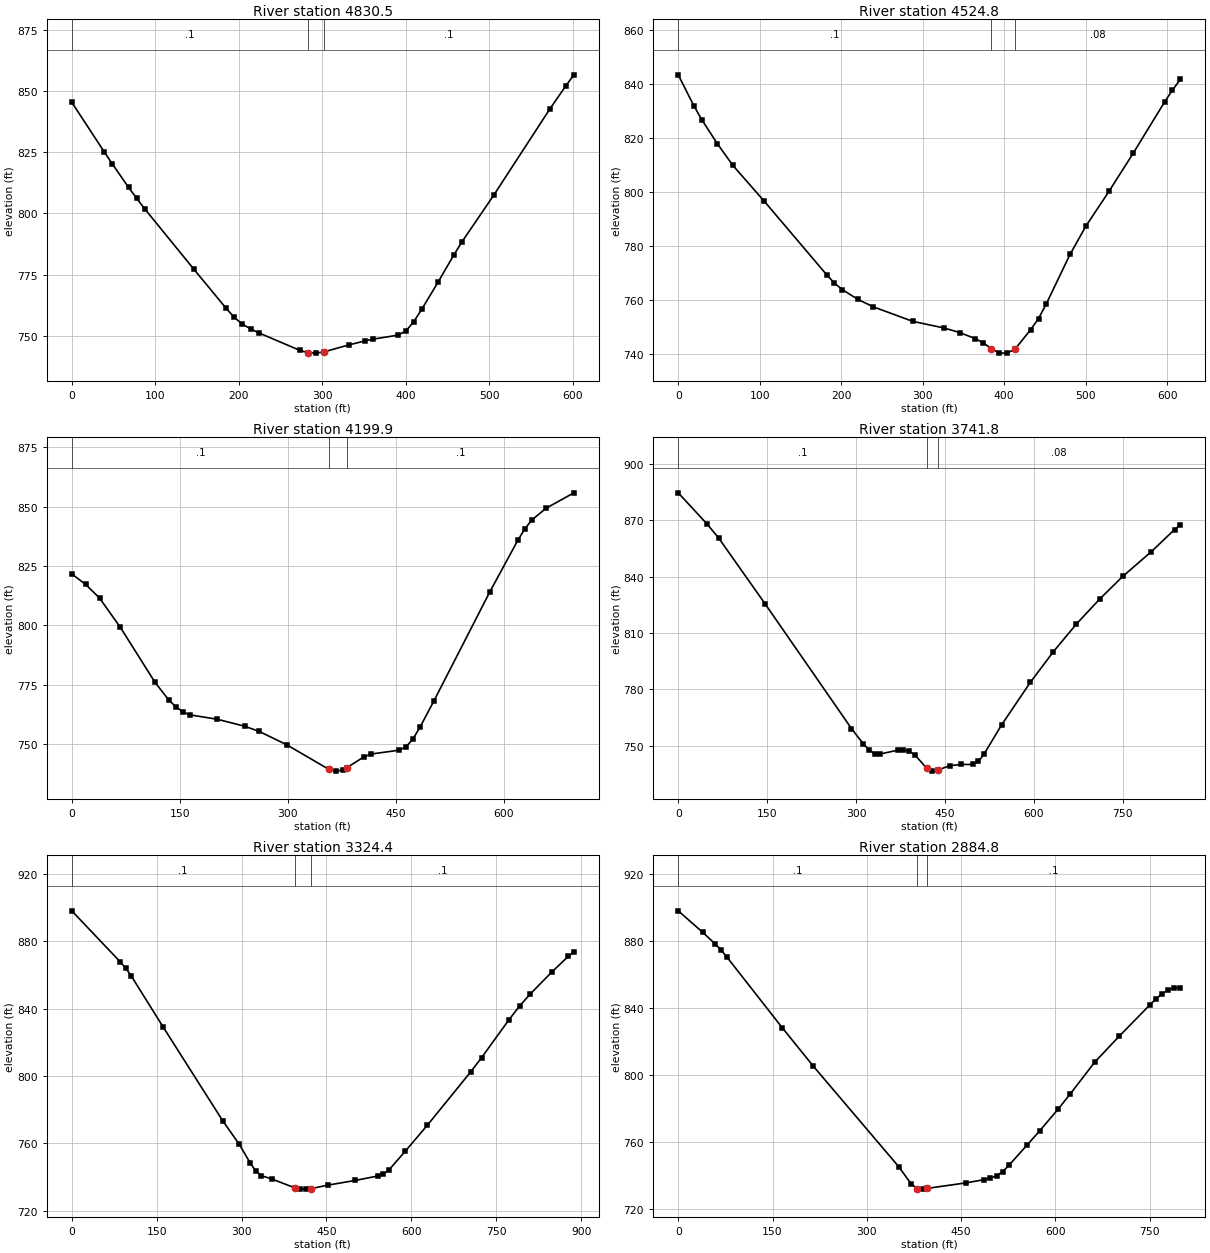
Type RM Length L Ch R = 1 ,4830.5  ,302.5,305.7,306.8
XS GIS Cut Line= 4
     1590135.369      315877.368     1590134.067      316081.795
      1590148.39      316277.108     1590201.775      316471.118
#Sta/Elev= 30
       0  845.37    38.9  825.11    48.7  820.12    68.1  810.57    77.9  806.07
    87.6  801.74     146  777.29     185  761.18   194.7  757.49   204.4  754.74
   214.2  752.81     224  751.19     273  744.06   282.5  743.09   292.6   742.9
   302.4  743.43   331.7  746.24   351.3  747.89   361.1  748.62   390.5  750.22
   400.3  751.93   409.8  755.78   419.4  760.87   438.6  771.76   457.8  783.04
   467.3  788.28   505.7   807.5   572.7   842.6   591.9  852.08   601.5  856.58
#Mann= 3 , 0 , 0
       0      .1       0   282.5    .045       0   302.4      .1       0
Bank Sta=282.5,302.4
XS Rating Curve= 0 ,0
Exp/Cntr=0.3,0.1

Type RM Length L Ch R = 1 ,4524.8  ,317.7,325,331.7
XS GIS Cut Line= 3
     1589972.753      315860.433     1589879.437      316142.551
     1589879.437      316461.561
#Sta/Elev= 30
       0  843.35    19.2  831.86    28.8  826.78    47.9  817.88    67.1  809.78
   105.4  796.59   182.1  769.31   191.7  766.18   201.3  763.81   220.5  760.15
   239.6  757.39   287.6  752.05   326.2  749.57   345.5  747.88   364.8   745.6
   374.5  744.04   384.2  741.89   393.8  740.31   403.5  740.26   413.2  741.69
   432.5  748.95   442.2  753.07   451.8  758.56   480.8  776.81   500.2  787.24
   529.2  800.45   558.2  814.21   596.8  833.25   606.5  837.68   616.2  841.62
#Mann= 3 , 0 , 0
       0      .1       0   384.2    .045       0   413.2     .08       0
Bank Sta=384.2,413.2
XS Rating Curve= 0 ,0
Exp/Cntr=0.3,0.1

Type RM Length L Ch R = 1 ,4199.9  ,455.2,458.1,459.6
XS GIS Cut Line= 3
     1589823.013      315836.561     1589625.316      316047.201
     1589497.348       316434.66
#Sta/Elev= 30
       0  821.64    19.3  817.21    38.5   811.5    67.4  799.17   115.6  775.99
   134.8  768.52   144.4  765.75   154.1   763.6   163.7  762.34   202.2  760.46
   240.7  757.47     260  755.37   298.6   749.7   356.9  739.37   366.6  738.64
   376.3   739.1   381.6  740.04   405.5  744.64   415.2  745.82     454  747.44
   463.8  748.82   473.5  752.11   483.2  757.05   502.6  768.15   580.3  814.11
   619.2  835.84   628.9  840.62   638.6  844.34   658.1  849.24   696.9  855.78
#Mann= 3 , 0 , 0
       0      .1       0   356.9    .045       0   381.6      .1       0
Bank Sta=356.9,381.6
XS Rating Curve= 0 ,0
Exp/Cntr=0.3,0.1

Type RM Length L Ch R = 1 ,3741.8  ,402.9,417.4,431.3
XS GIS Cut Line= 3
     1589416.248      315556.831     1589235.859       315956.51
     1589082.085      316335.149
#Sta/Elev= 30
       0  884.54    48.7  867.93    68.2  860.51   146.2  825.66   292.3  759.18
   311.8   751.2   321.6   747.9   331.3  745.81   341.1  745.65   370.3  747.66
     380  747.82   389.8   747.1   399.5  745.06     419  738.17   428.6  736.52
   438.5  737.13     458  739.42   477.4  740.06   496.9  740.08   506.6  741.68
   516.3  745.74   545.5  761.04   594.2  783.79   633.1  800.07     672  814.81
     711  827.98   749.9  840.05   798.5   853.3   837.4  864.99   847.2  867.49
#Mann= 3 , 0 , 0
       0      .1       0     419    .045       0   438.5     .08       0
Bank Sta=419,438.5
XS Rating Curve= 0 ,0
Exp/Cntr=0.3,0.1

Type RM Length L Ch R = 1 ,3324.4  ,442.9,439.5,436.4
XS GIS Cut Line= 4
     1589213.204      315422.065     1589067.805      315645.589
     1588753.135       315823.54     1588553.482      315988.471
#Sta/Elev= 30
       0  898.07    85.7  867.74    95.2  864.08   104.8  859.52   161.9  828.81
   266.6  773.41     296  759.34   315.5  748.15   325.3  743.45     335  740.73
   354.6  738.66   393.7  733.54   403.4  732.88   413.2  732.75     423  733.05
   452.3  735.12   501.1  737.92   540.2  740.52     550  741.54   559.8  743.92
   589.1   755.2   628.2  770.68   704.9  802.43   724.1  810.88     772  833.14
   791.2  841.49   810.4  848.78   848.8  861.94   877.5  871.08   887.1  873.63
#Mann= 3 , 0 , 0
       0      .1       0   393.7    .045       0     423      .1       0
Bank Sta=393.7,423
XS Rating Curve= 0 ,0
Exp/Cntr=0.3,0.1

Type RM Length L Ch R = 1 ,2884.8  ,516,523.7,529.6
XS GIS Cut Line= 2
     1588984.455      315133.394     1588354.247      315624.279
#Sta/Elev= 30
       0  897.79      39  884.93    58.4  878.17    68.2  874.37    77.9  869.96
   165.6  827.95   214.3  805.33   350.7  745.11   370.2  734.96   379.9  732.01
   389.7  731.66   395.8  732.09   457.9   735.4   487.1  737.33   496.8  738.25
   506.6  739.64   516.3  742.14   526.1  745.88   555.3  758.09   574.8  766.35
     604  779.23   623.5  788.38   662.4  807.36   701.4  822.86   750.1  841.55
   759.9  845.14   769.6   848.2   779.4   850.5   789.1   851.9   798.8  851.88
#Mann= 3 , 0 , 0
       0      .1       0   379.9    .045       0   395.8      .1       0
Bank Sta=379.9,395.8
XS Rating Curve= 0 ,0
Exp/Cntr=0.3,0.1