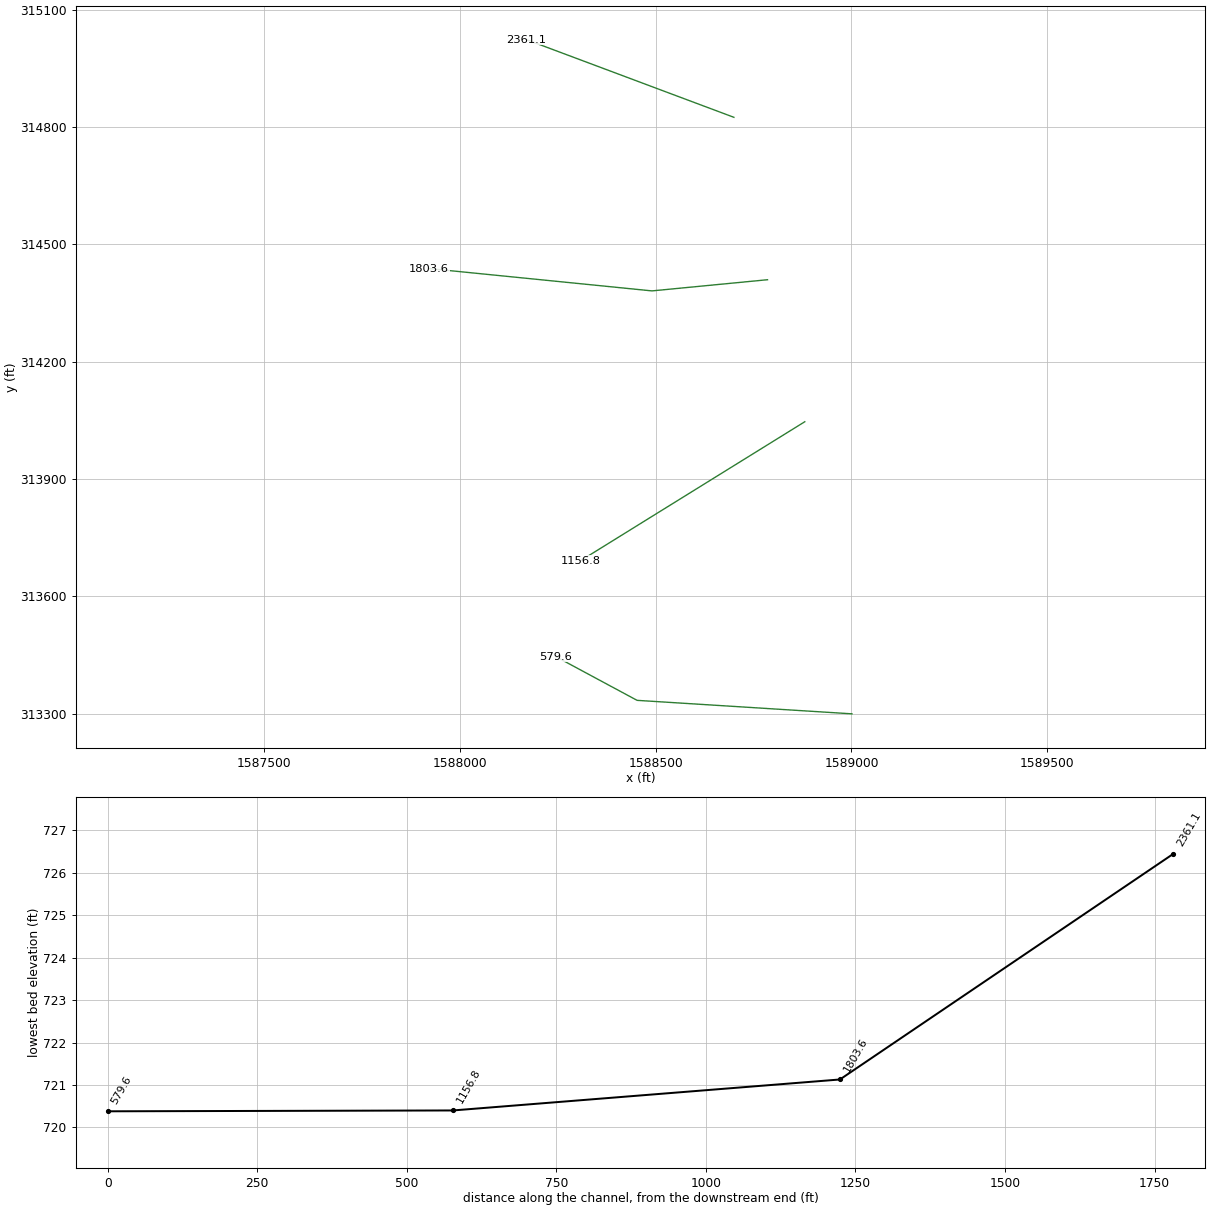
HEC-RAS study CMPMTKRN.prj: CMPMTKRN

--- CMPMTKRN.g01 (geometry) --- (continued)

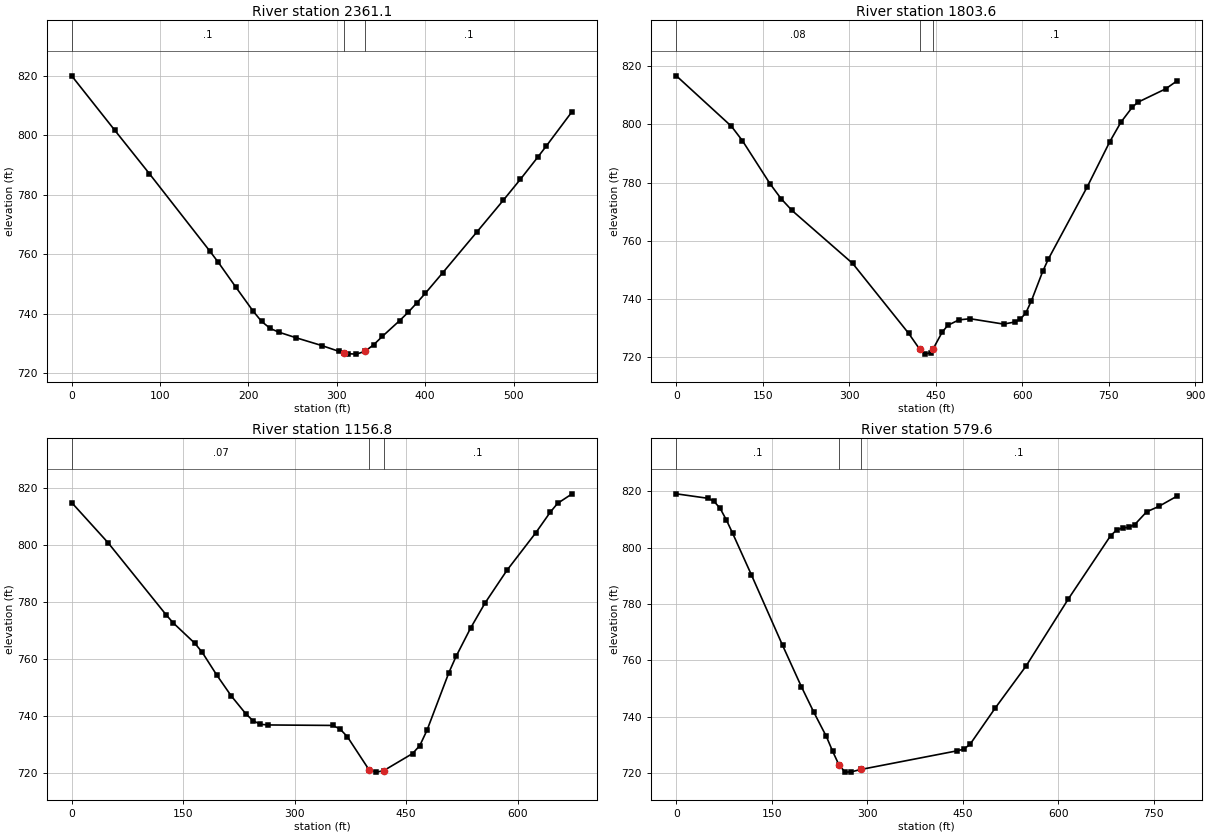
Type RM Length L Ch R = 1 ,2361.1  ,551,557.5,562.5
XS GIS Cut Line= 2
     1588699.997      314824.642     1588169.774      315023.405
#Sta/Elev= 30
       0     820    48.8  801.68    87.9  787.11   156.2  761.12     166  757.26
   185.5  749.06     205  741.02   214.8  737.46   224.6  735.09   234.3  733.84
   253.8  731.96   283.1  729.32   302.6  727.36   308.5   726.9   312.4  726.59
   322.2  726.45   331.9   727.4   341.7  729.61   351.5  732.41     371   737.7
   380.8  740.54   390.5  743.67   400.3  746.97   419.8   753.8   458.9  767.67
   488.2  778.12   507.7  785.23   527.2  792.61     537   796.4   566.2     808
#Mann= 3 , 0 , 0
       0      .1       0   308.5    .045       0   331.9      .1       0
Bank Sta=308.5,331.9
XS Rating Curve= 0 ,0
Exp/Cntr=0.3,0.1

Type RM Length L Ch R = 1 ,1803.6  ,631.7,646.8,661.2
XS GIS Cut Line= 3
     1588785.803      314409.511     1588490.972      314380.979
     1587921.917      314438.043
#Sta/Elev= 30
       0  816.71    95.6  799.37   114.7  794.41   162.4  779.68   181.6  774.53
   200.7  770.46   305.9  752.27   402.8  728.31   422.2   722.8   431.9  721.13
   441.6  721.67   445.3  722.89     461  728.61   470.7  730.99   490.1  732.89
   509.5  733.29   567.6  731.45     587  732.15   596.7   733.1   606.4  735.33
   616.1  739.52   635.5  749.51   645.2  753.74     713  778.67   751.8  794.05
   771.2  800.78   790.6  805.84   800.3  807.61   848.7  812.22   868.1   814.9
#Mann= 3 , 0 , 0
       0     .08       0   422.2    .045       0   445.3      .1       0
Bank Sta=422.2,445.3
XS Rating Curve= 0 ,0
Exp/Cntr=0.3,0.1

Type RM Length L Ch R = 1 ,1156.8  ,590.2,577.2,564
XS GIS Cut Line= 2
      1588880.91       314046.52     1588308.684      313691.455
#Sta/Elev= 30
       0  814.72    48.8  800.72   126.9  775.51   136.6  772.63   165.9  765.44
   175.7   762.3   195.2  754.38   214.7  747.07   234.2  740.85     244  738.39
   253.8  737.16   263.5  736.91   351.4  736.74   361.1  735.49   370.9  732.81
   400.2  721.19   409.9   720.4   419.6  720.88   458.7   726.9   468.5  729.71
   478.2   735.1   507.5  755.18   517.3  760.92   536.8  770.81   556.3  779.61
   585.6  790.99   624.6  804.19   644.2  811.44   653.9  814.46   673.4  817.79
#Mann= 3 , 0 , 0
       0     .07       0   400.2    .045       0   419.6      .1       0
Bank Sta=400.2,419.6
XS Rating Curve= 0 ,0
Exp/Cntr=0.3,0.1

Type RM Length L Ch R = 1 ,579.6   ,584.1,579.6,574.8
XS GIS Cut Line= 3
     1589001.378      313299.932     1588452.851       313334.39
     1588244.713      313446.465
#Sta/Elev= 30
       0  819.03    49.1  817.46    58.9  816.44    68.7   813.9    78.5  809.81
    88.3   805.1   117.8  790.36   166.8  765.35   196.3  750.72   215.9  741.63
   235.6  733.03   245.4  727.82   255.2  723.04     265  720.38   274.7  720.47
   289.7  721.32   441.6  727.96   451.5  728.53   461.3  730.23   500.5  742.98
   549.6  758.09   615.8   781.8     682  804.16   691.4   806.2   700.9  806.92
   710.4  807.17   719.8  808.09   738.7  812.66   757.6  814.55     786  818.16
#Mann= 3 , 0 , 0
       0      .1       0   255.2    .045       0   289.7      .1       0
Bank Sta=255.2,289.7
XS Rating Curve= 0 ,0
Exp/Cntr=0.3,0.1

Chan Stop Cuts=-1
Use User Specified Reach Order=0
Composite Channel Slope=5